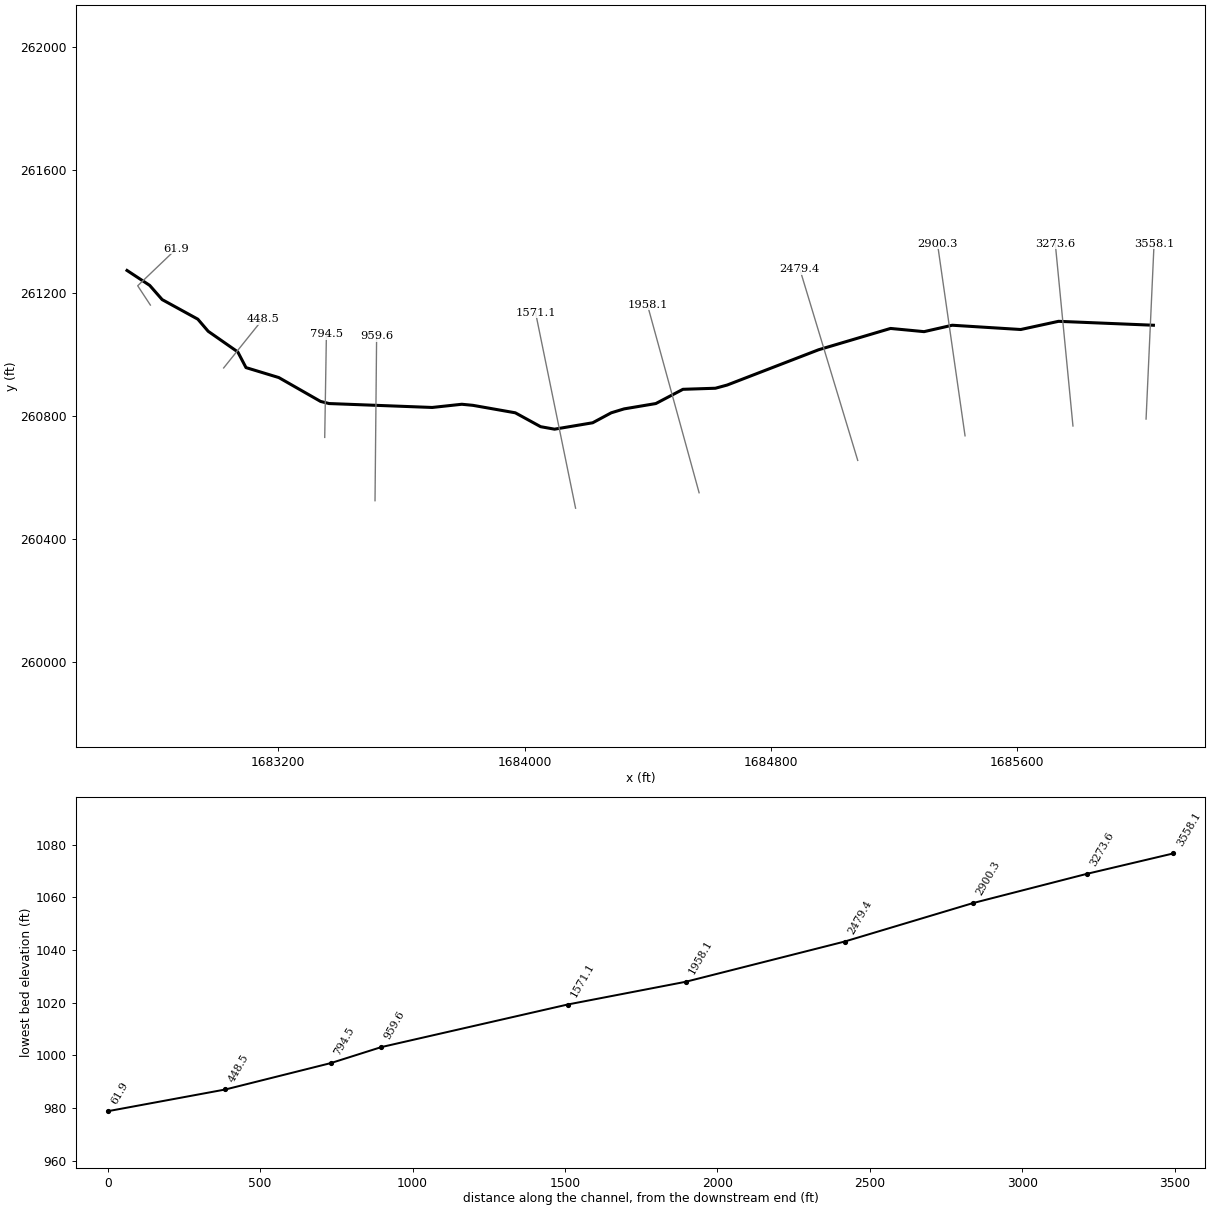
--- CONLYBRNCH.prj (project) ---

Proj Title=CONLYBRNCH
Current Plan=p01
Default Exp/Contr=0,0
English Units
Geom File=g01
Flow File=f01
Plan File=p01
BEGIN DESCRIPTION:
END DESCRIPTION:
DSS Export Rating Curves= 0
DSS Export Rating Curve Sorted= 0
DSS Export Volume Flow Curves= 0
DXF OffsetX= 0
DXF OffsetY= 0
DXF ScaleX= 0
DXF ScaleY= 0

--- CONLYBRNCH.p01 (plan) ---

Plan Title=Floodplain
Program Version=4.00
Geom File=g01
Flow File=f01
K Sum by GR=0
Std Step Tol=0.01
Critical Tol=0.01
Num of Std Step Trials=20
Max Error Tol=0.3
Flow Tol Ratio=0.001
Split Flow NTrial=30
Split Flow Tol=0.02
Split Flow Ratio=0.02
Log Output Level=0
Friction Slope Method=1
Unsteady Friction Slope Method=2
Unsteady Bridges Friction Slope Method=1
Global Log Level=0
CheckData=False
Run HTab=0
Run UNet=0
Run PostProcess=0
UNET Theta=0
UNET Theta Warmup=0
UNET ZTol=0
UNET ZSATol=0
UNET MxIter=0
UNET MaxInSteps=0
UNET DtIC=0
UNET DtMin=0
UNET MaxCRTS=0
UNET WFStab=0
UNET SFStab=0
UNET WFX=0
UNET SFX=0
UNET DSS MLevel=0
UNET DZMax Abort=0
UNET Convert EG Bridges=0
UNET Use Existing IB Tables=0
UNET Froude Limit=0
UNET Froude Power=0
Write IC File=0
Echo Input=False
Echo Output=False
Write Detailed=0

--- CONLYBRNCH.f01 (steady flow) ---

Flow Title=NFF Regression Equation
Program Version=4.00
Number of Profiles=1
Profile Names=P100yr
River Rch & RM=CONLYBRNCH,Main      ,3558.1
891.6806
River Rch & RM=CONLYBRNCH,Main      ,61.9
967.8691
Boundary for River Rch & Prof#=CONLYBRNCH,Main      ,1
Up Type=0
Dn Type=3
Dn Slope=0.031831

--- CONLYBRNCH.g01 (geometry) ---

Geom Title=USGS 10m DEM
Program Version=4.10

River Reach=CONLYBRNCH      ,Main
Reach XY= 30
     1686042.012      261095.559      1685733.93      261108.299
      1685611.16      261081.661     1685388.785      261095.559
     1685297.287      261074.711     1685188.416      261085.135
     1684954.459      261015.643     1684657.959      260900.981
     1684619.738      260890.557     1684514.341      260887.083
     1684426.318      260840.754     1684323.238      260823.381
     1684281.543      260810.641     1684221.316      260778.211
     1684097.389      260757.364     1684052.219      260765.471
     1683969.986      260810.641      1683832.16      260834.963
     1683796.256      260838.438     1683700.125      260828.014
     1683365.404      260840.754     1683337.607      260847.704
     1683202.097      260925.303     1683095.543      260957.733
     1683068.904      261008.694     1682972.773       261075.87
     1682939.185      261115.248     1682823.365       261178.95
     1682782.828      261225.278     1682709.233      261273.821

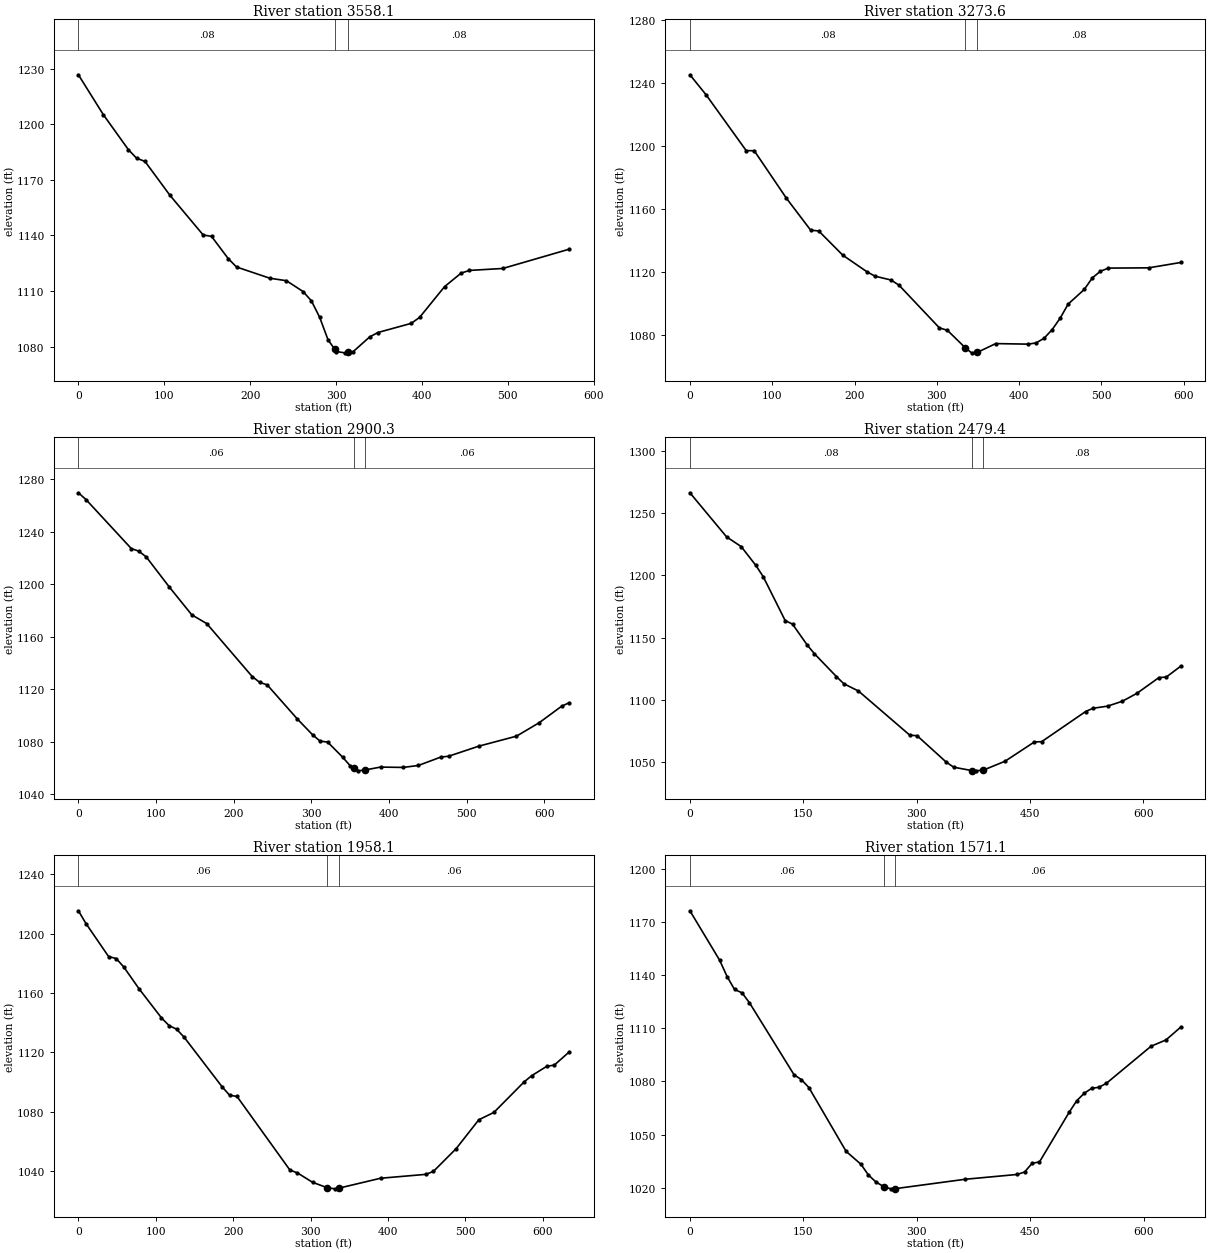
Type RM Length L Ch R = 1 ,3558.1  ,281.1,284.5,287.5
XS GIS Cut Line= 2
     1686018.129       260790.34     1686044.085      261361.425
#Sta/Elev= 30
       0 1226.75    29.1 1205.17    58.1  1186.4    67.8 1181.69    77.5    1180
   106.6 1161.68   145.3 1140.26     155 1139.53   174.4 1127.55   184.1 1122.99
   222.9 1116.92   242.2 1115.58   261.6 1109.74   271.3 1104.72     281 1095.77
   290.7 1083.62   298.5 1078.59   300.4 1077.36   310.1 1076.64   313.5 1076.84
   319.8 1077.22   339.1 1085.21   348.8 1087.62   387.6 1092.56   397.3 1095.77
   426.3 1112.34   445.7  1119.7   455.4 1121.13   494.2 1122.19   571.7 1132.62
#Mann= 3 , 0 , 0
       0     .08       0   298.5    .045       0   313.5     .08       0
Bank Sta=298.5,313.5
XS Rating Curve= 0 ,0
Exp/Cntr=0.3,0.1

Type RM Length L Ch R = 1 ,3273.6  ,372.2,373.2,374.3
XS GIS Cut Line= 2
     1685780.733      260767.714     1685723.275      261361.425
#Sta/Elev= 30
       0 1245.32    19.6 1232.65    68.4 1197.19    78.2 1197.11   117.3 1166.95
   146.7 1146.72   156.5 1146.22   185.8 1130.82   215.1 1120.32   224.9 1117.52
   244.5 1115.06   254.2 1111.73   303.1 1084.72   312.9 1083.15   334.4 1072.16
   342.2 1068.87   349.4 1069.23   371.6 1074.74   410.7 1074.39   420.5 1075.14
   430.2 1078.07     440 1083.52   449.8 1090.83   459.6 1099.83   479.1 1109.08
   488.9 1116.41   498.7 1120.62   508.5 1122.64   557.4 1122.81   596.5 1126.23
#Mann= 3 , 0 , 0
       0     .08       0   334.4    .045       0   349.4     .08       0
Bank Sta=334.4,349.4
XS Rating Curve= 0 ,0
Exp/Cntr=0.3,0.1

Type RM Length L Ch R = 1 ,2900.3  ,417.4,420.9,424.2
XS GIS Cut Line= 2
     1685430.341       260735.74     1685340.735      261361.425
#Sta/Elev= 30
       0  1269.6     9.7 1264.48    68.1 1227.11    77.8 1225.12    87.5 1220.64
   116.7 1198.08   145.9 1176.66   165.3 1169.92   223.7 1129.65   233.4 1125.19
   243.1 1123.24     282 1097.21   301.4 1085.32   311.2 1080.42   320.9  1079.7
   340.3 1068.13   350.1 1061.54   354.4 1059.88   359.8 1057.79   369.4  1058.5
     389 1060.65   418.1 1060.39   437.6 1061.87   466.8 1068.32   476.5 1068.88
   515.4 1076.57     564  1084.2   593.2 1094.43   622.3 1107.08   632.1 1109.71
#Mann= 3 , 0 , 0
       0     .06       0   354.4    .045       0   369.4     .06       0
Bank Sta=354.4,369.4
XS Rating Curve= 0 ,0
Exp/Cntr=0.3,0.1

Type RM Length L Ch R = 1 ,2479.4  ,521.7,521.3,520.4
XS GIS Cut Line= 2
     1685081.877      260655.764     1684893.949      261277.848
#Sta/Elev= 30
       0 1266.19    48.5 1230.86    67.9 1223.03    87.3 1207.94      97 1198.96
   126.1 1163.72   135.8 1160.86   155.2 1144.16   164.9 1137.06     194 1118.74
   203.7 1113.06   223.1 1107.21     291 1071.81   300.7 1071.38   339.5 1050.06
   349.2 1046.11   373.4 1043.37   378.3  1043.2   388.4 1043.77   417.1 1050.91
   455.9 1066.35   465.6 1066.59   523.8 1090.78   533.5 1093.37   552.9  1095.1
   572.3    1099   591.6 1105.34   620.8    1118   630.4 1118.37   649.8 1127.19
#Mann= 3 , 0 , 0
       0     .08       0   373.4    .045       0   388.4     .08       0
Bank Sta=373.4,388.4
XS Rating Curve= 0 ,0
Exp/Cntr=0.3,0.1

Type RM Length L Ch R = 1 ,1958.1  ,388.5,387,385.5
XS GIS Cut Line= 2
     1684566.827      260550.517     1684398.966      261162.138
#Sta/Elev= 30
       0 1215.37     9.8 1206.74      39 1184.53    48.8  1183.2    58.6 1177.49
    78.1 1162.96   107.3 1143.18   117.1    1138   126.8 1135.57   136.6 1130.14
   185.4 1096.87   195.2 1091.09   204.9  1090.2   273.2 1040.61     283 1038.66
   302.5 1032.34   321.7 1028.64   331.8 1027.94   336.7 1028.43   390.3 1035.08
   448.8  1037.7   458.6 1039.69   487.9 1055.01   517.2 1074.48   536.7 1079.46
   575.7 1099.99   585.4 1104.17     605 1110.53   614.7 1111.33   634.2 1120.31
#Mann= 3 , 0 , 0
       0     .06       0   321.7    .045       0   336.7     .06       0
Bank Sta=321.7,336.7
XS Rating Curve= 0 ,0
Exp/Cntr=0.3,0.1

Type RM Length L Ch R = 1 ,1571.1  ,616.3,611.5,606.5
XS GIS Cut Line= 2
     1684165.707      260500.286     1684035.767      261136.547
#Sta/Elev= 30
       0 1176.35    39.4 1148.39    49.2 1139.21      59 1131.92    68.9 1130.03
    78.7 1124.47   137.8 1083.71   147.6 1080.96   157.4  1076.5   206.6  1040.5
   226.3 1033.17   236.1 1027.15     246 1023.21   256.6 1020.49   265.7 1019.32
   271.6 1019.42     364 1024.72   432.9 1027.44   442.8 1028.85   452.6 1033.74
   462.4 1034.52   501.8 1062.67   511.6 1069.03   521.5 1073.27   531.3 1076.04
   541.2 1076.72     551 1078.96     610 1099.86   629.7  1103.4   649.4 1110.72
#Mann= 3 , 0 , 0
       0     .06       0   256.6    .045       0   271.6     .06       0
Bank Sta=256.6,271.6
XS Rating Curve= 0 ,0
Exp/Cntr=0.3,0.1

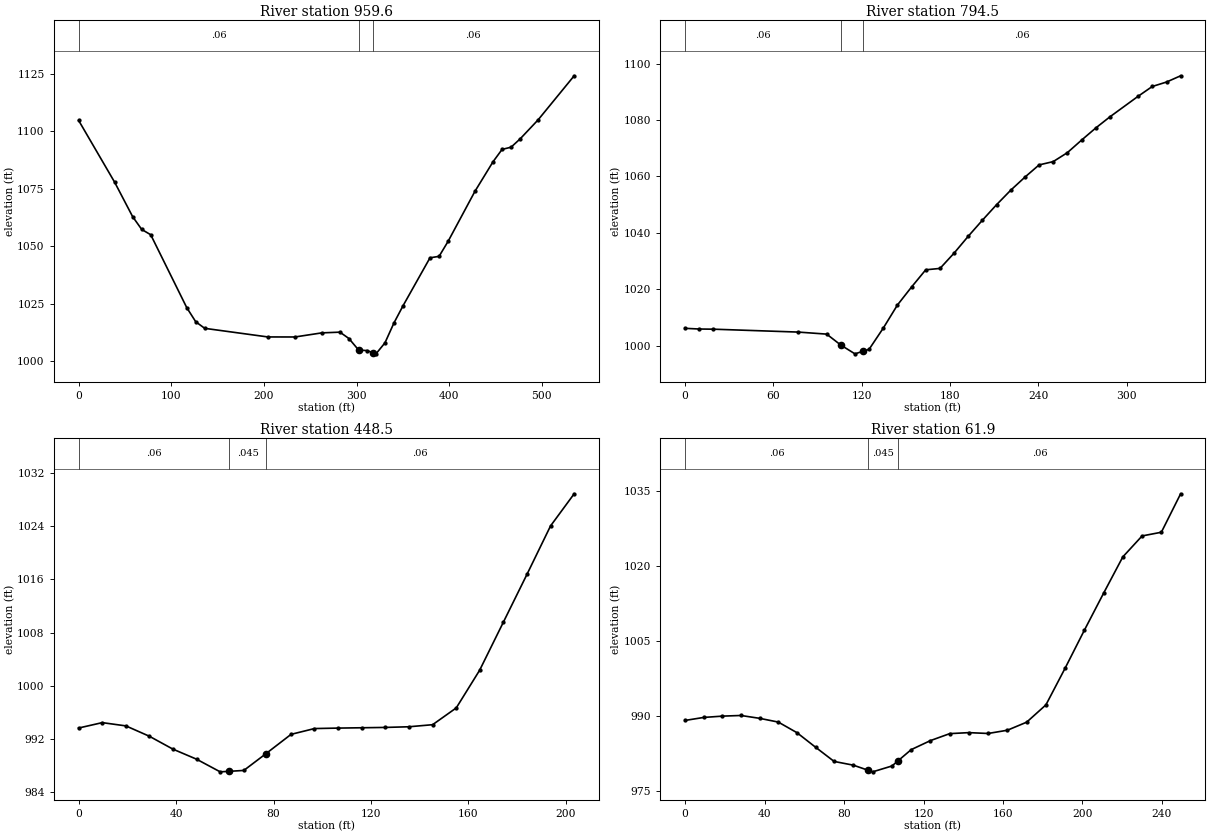
Type RM Length L Ch R = 1 ,959.6   ,165.1,165.1,165
XS GIS Cut Line= 2
     1683514.505      260524.602     1683519.674      261059.386
#Sta/Elev= 30
       0 1104.68    38.9 1077.78    58.3 1062.82    68.1 1057.26    77.8 1054.96
   116.7 1023.24   126.4  1017.1   136.1 1014.25   204.2 1010.51   233.4 1010.49
   262.5 1012.28     282 1012.59   291.7 1009.83   302.2  1004.8   311.2 1004.58
   317.2  1003.7   320.9 1003.16   330.6 1007.94   340.3 1016.59   350.1 1024.07
   379.2 1044.93     389 1045.56   398.7 1052.06   427.8 1073.91   447.3 1086.75
     457 1092.08   466.7 1093.04   476.5 1096.66   495.9 1104.94   534.8  1124.1
#Mann= 3 , 0 , 0
       0     .06       0   302.2    .045       0   317.2     .06       0
Bank Sta=302.2,317.2
XS Rating Curve= 0 ,0
Exp/Cntr=0.3,0.1

Type RM Length L Ch R = 1 ,794.5   ,361.1,346,330.7
XS GIS Cut Line= 2
     1683351.196      260730.592      1683356.67      261067.231
#Sta/Elev= 30
       0 1006.15     9.6 1005.91    19.2 1005.85      77 1004.82    96.2  1004.1
   105.8 1000.22   115.4  997.11   120.8     998     125   998.7   134.7 1006.27
   144.3 1014.44   153.9 1020.82   163.5  1026.9   173.2 1027.39   182.8 1032.83
   192.4  1038.8     202 1044.48   211.6 1049.96   221.2 1055.09   230.9 1059.75
   240.5 1064.08   250.1 1065.25   259.7 1068.41   269.4 1072.88     279 1077.16
   288.6 1081.11   307.8 1088.41   317.4 1091.88   327.1 1093.46   336.7 1095.68
#Mann= 3 , 0 , 0
       0     .06       0   105.8    .045       0   120.8     .06       0
Bank Sta=105.8,120.8
XS Rating Curve= 0 ,0
Exp/Cntr=0.3,0.1

Type RM Length L Ch R = 1 ,448.5   ,389.5,386.5,383.4
XS GIS Cut Line= 2
     1683023.012      260956.586     1683150.062      261115.398
#Sta/Elev= 24
       0  993.67     9.7  994.48    19.4  993.99      29  992.44    38.7   990.5
    48.4  988.99    58.1  987.09    61.9  987.17    67.8   987.3    76.9  989.82
    77.5  989.99    87.2  992.72    96.8  993.59   106.5  993.66   116.2  993.71
   125.9  993.76   135.6  993.86   145.3  994.17     155  996.69   164.6 1002.35
   174.3 1009.54     184 1016.73   193.7 1024.02   203.4 1028.85
#Mann= 3 , 0 , 0
       0     .06       0    61.9    .045       0    76.9     .06       0
Bank Sta=61.9,76.9
XS Rating Curve= 0 ,0
Exp/Cntr=0.3,0.1

Type RM Length L Ch R = 1 ,61.9    ,55.3,61.9,68.1
XS GIS Cut Line= 3
     1682785.055      261161.204     1682743.885      261223.945
     1682869.784      261344.548
#Sta/Elev= 29
       0  989.11     9.4  989.71    18.8  989.97    28.1   990.1    37.5  989.53
    46.9  988.78    56.3  986.66    65.7  983.74      75  980.91    84.7  980.16
    92.3  979.12    94.4  978.83   104.1     980   107.3  981.08   113.8  983.27
   123.5  985.08   133.2  986.47   142.8  986.67   152.5   986.5   162.2  987.15
   171.9  988.76   181.6  992.22   191.3  999.59     201 1007.19   210.6 1014.53
   220.3 1021.81     230    1026   239.7 1026.74   249.4 1034.43
#Mann= 3 , 0 , 0
       0     .06       0    92.3    .045       0   107.3     .06       0
Bank Sta=92.3,107.3
XS Rating Curve= 0 ,0
Exp/Cntr=0.3,0.1

Chan Stop Cuts=-1
Use User Specified Reach Order=0
Composite Channel Slope=5